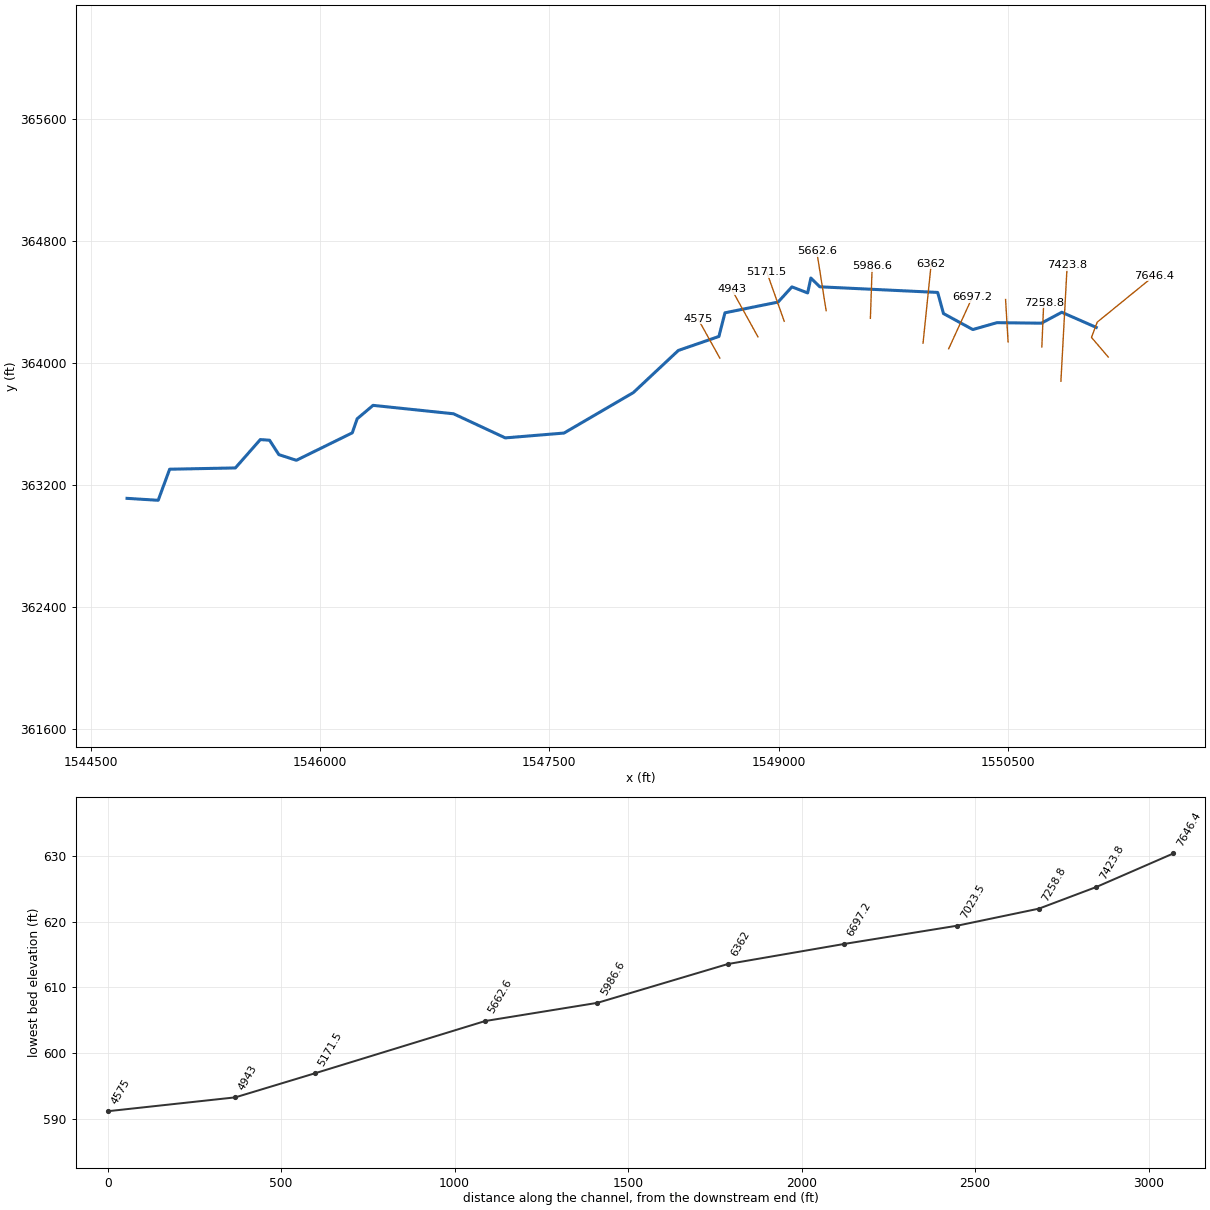
--- HORSECR.prj (project) ---

Proj Title=HORSECR
Current Plan=p01
Default Exp/Contr=0,0
English Units
Geom File=g01
Flow File=f01
Plan File=p01
BEGIN DESCRIPTION:
END DESCRIPTION:
DSS Export Rating Curves= 0
DSS Export Rating Curve Sorted= 0
DSS Export Volume Flow Curves= 0
DXF OffsetX= 0
DXF OffsetY= 0
DXF ScaleX= 0
DXF ScaleY= 0

--- HORSECR.p01 (plan) ---

Plan Title=Floodplain
Program Version=4.00
Geom File=g01
Flow File=f01
K Sum by GR=0
Std Step Tol=0.01
Critical Tol=0.01
Num of Std Step Trials=20
Max Error Tol=0.3
Flow Tol Ratio=0.001
Split Flow NTrial=30
Split Flow Tol=0.02
Split Flow Ratio=0.02
Log Output Level=0
Friction Slope Method=1
Unsteady Friction Slope Method=2
Unsteady Bridges Friction Slope Method=1
Global Log Level=0
CheckData=False
Run HTab=0
Run UNet=0
Run PostProcess=0
UNET Theta=0
UNET Theta Warmup=0
UNET ZTol=0
UNET ZSATol=0
UNET MxIter=0
UNET MaxInSteps=0
UNET DtIC=0
UNET DtMin=0
UNET MaxCRTS=0
UNET WFStab=0
UNET SFStab=0
UNET WFX=0
UNET SFX=0
UNET DSS MLevel=0
UNET DZMax Abort=0
UNET Convert EG Bridges=0
UNET Use Existing IB Tables=0
UNET Froude Limit=0
UNET Froude Power=0
Write IC File=0
Echo Input=False
Echo Output=False
Write Detailed=0

--- HORSECR.f01 (steady flow) ---

Flow Title=NFF Regression Equation
Program Version=4.00
Number of Profiles=1
Profile Names=P100yr
River Rch & RM=HORSECR,Main      ,7646.4
452.1448
River Rch & RM=HORSECR,Main      ,5986.6
493.3640
Boundary for River Rch & Prof#=HORSECR,Main      ,1
Up Type=0
Dn Type=3
Dn Slope=0.012625

--- HORSECR.g01 (geometry) ---

Geom Title=Geometry
Program Version=4.00

River Reach=HORSECR         ,Main
Reach XY= 30
     1551077.931      364231.499     1550852.498      364330.812
      1550719.23      364259.135     1550427.848      364262.486
     1550270.287      364217.483     1550078.642      364322.157
     1550040.517      364460.739     1549269.357      364497.621
      1549210.93      364555.193     1549189.973      364457.475
     1549087.058      364497.186     1548996.447       364397.51
     1548648.921      364327.208     1548609.425       364172.15
      1548344.13      364080.473     1548049.595      363804.154
     1547596.071       363538.89     1547211.885      363507.158
     1546873.118      363665.252     1546346.854      363720.392
     1546242.693      363632.416     1546210.895      363540.366
     1545845.088      363360.315     1545730.295      363397.541
     1545669.653      363491.909     1545609.081      363496.103
     1545446.014      363310.223     1545015.952      363301.837
     1544941.017      363098.079     1544737.125      363110.837

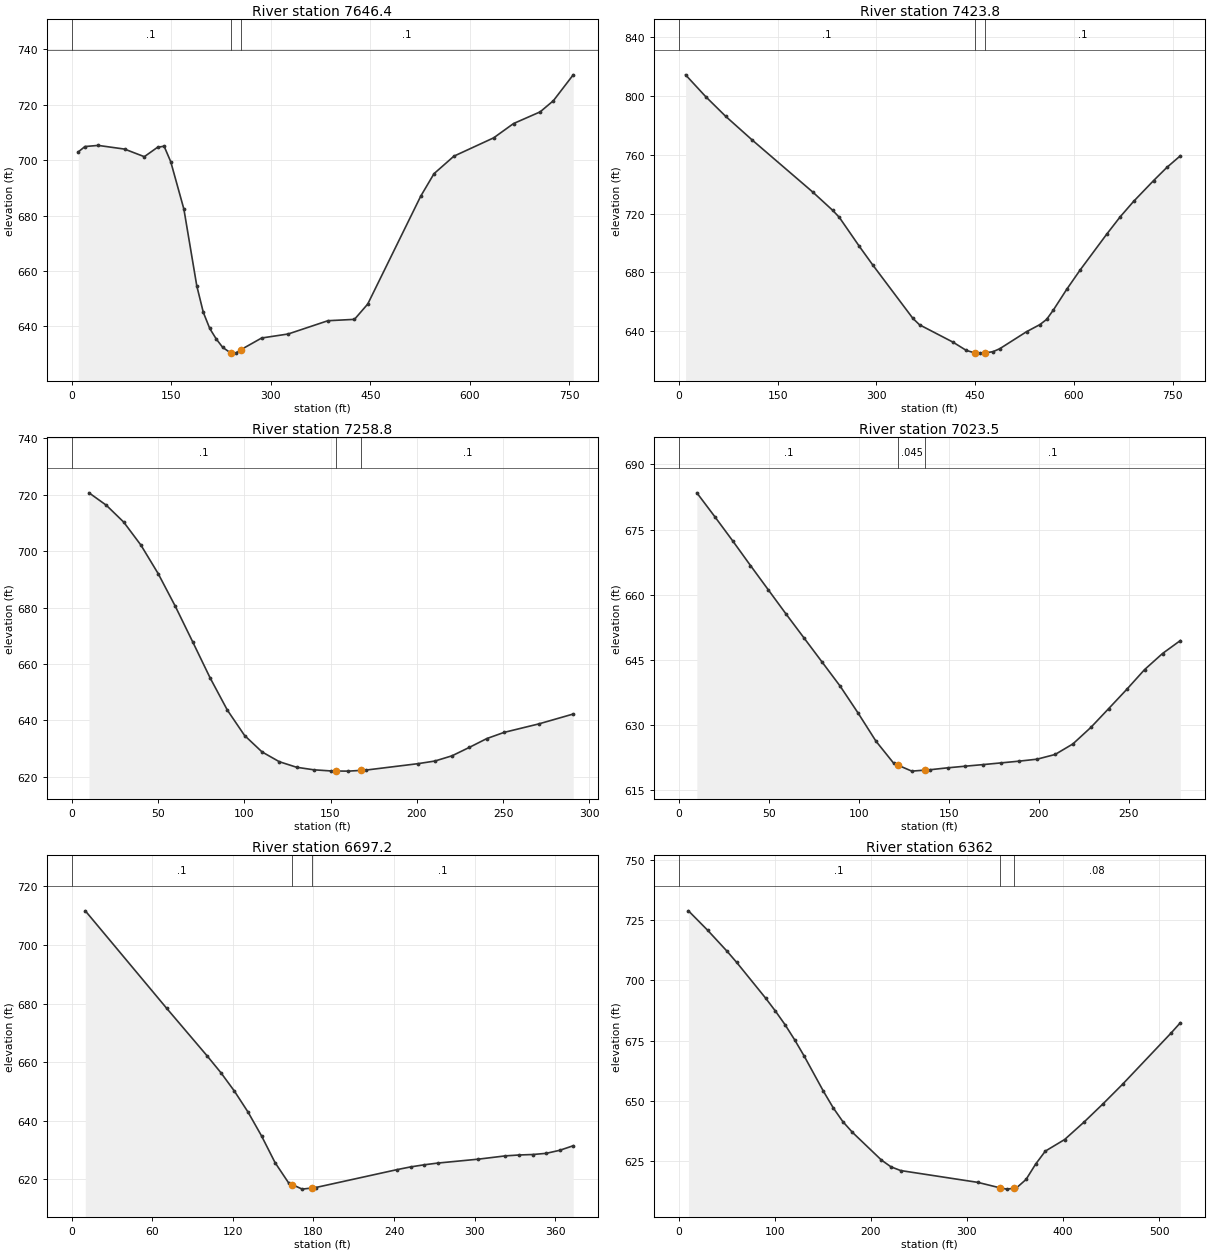
Type RM Length L Ch R = 1 ,7646.4  ,215.4,222.6,229.8
XS GIS Cut Line= 4
     1551156.547      364037.314     1551046.826      364165.913
     1551084.579      364266.197     1551456.218      364569.407
#Sta/Elev= 30
     9.9  703.02    19.9  704.94    39.8  705.35    79.6  704.02   109.4  701.28
   129.3  704.67   139.2  705.07   149.2  699.46     169  682.37   188.5  654.59
   198.3  645.07     208  639.26   217.8  635.46   227.5  632.44   239.5  630.43
     247  630.36   254.5  631.54   286.2  635.82   326.2  637.27   386.1  642.06
   426.1  642.55   446.1  648.08     526  687.04     546  695.15     576  701.47
   635.9  708.08   665.9  713.25   705.9  717.45   725.9  721.49   755.8  730.83
#Mann= 3 , 0 , 0
       0      .1       0   239.5    .045       0   254.5      .1       0
Bank Sta=239.5,254.5
XS Rating Curve= 0 ,0
Exp/Cntr=0.3,0.1

Type RM Length L Ch R = 1 ,7423.8  ,164.9,165,165
XS GIS Cut Line= 2
     1550846.833      363878.823     1550887.738      364639.653
#Sta/Elev= 30
    10.2  814.14    40.6  799.42    71.1     786   111.7  769.79   203.2  734.67
   233.7  722.17   243.8   717.4   274.3  697.67   294.6  685.08   355.6  648.82
   365.7  644.47   416.5   632.7   436.8  627.07   449.7   625.4   457.2  625.25
   464.7  625.32   477.5  626.27   487.6  628.26   528.3  639.81   548.6  644.64
   558.7  648.13   568.9  654.45   589.2  668.51   609.5  681.58   650.2  706.08
   670.5  717.76   690.8   728.2   721.3  742.38   741.6  751.37   761.9  759.18
#Mann= 3 , 0 , 0
       0      .1       0   449.7    .045       0   464.7      .1       0
Bank Sta=449.7,464.7
XS Rating Curve= 0 ,0
Exp/Cntr=0.3,0.1

Type RM Length L Ch R = 1 ,7258.8  ,232.9,235.4,237.9
XS GIS Cut Line= 2
     1550722.069        364103.8     1550734.341      364394.224
#Sta/Elev= 27
      10  720.71      20  716.33    30.1  710.34    40.1  702.16    50.1  692.05
    60.1  680.38    70.2  667.73    80.2  655.07    90.2  643.62   100.2  634.61
   110.3  628.79   120.3  625.32   130.3  623.35   140.3  622.44   150.4  622.03
   152.9  622.01   160.4  621.97   167.9  622.24   170.4  622.33   200.5   624.6
   210.5  625.55   220.5  627.42   230.5   630.4   240.6  633.52   250.6  635.71
   270.6   638.7   290.7  642.23
#Mann= 3 , 0 , 0
       0      .1       0   152.9    .045       0   167.9      .1       0
Bank Sta=152.9,167.9
XS Rating Curve= 0 ,0
Exp/Cntr=0.3,0.1

Type RM Length L Ch R = 1 ,7023.5  ,337.6,326.3,314.9
XS GIS Cut Line= 2
     1550501.183      364136.523     1550484.821      364414.677
#Sta/Elev= 30
      10  683.45    19.9     678    29.9   672.4    39.8  666.71    49.8  661.06
    59.7  655.47    69.7  649.95    79.6  644.48    89.6  638.95    99.5   632.8
   109.5  626.28   119.4  621.17   121.9  620.72   129.4  619.38   136.9  619.62
   139.3  619.69   149.3  620.14   159.2  620.52   169.2  620.89   179.1  621.28
   189.1  621.68     199  622.13     209  623.21   218.9  625.64   228.9  629.45
   238.8  633.78   248.8  638.19   258.7  642.74   268.7  646.46   278.6  649.44
#Mann= 3 , 0 , 0
       0      .1       0   121.9    .045       0   136.9      .1       0
Bank Sta=121.9,136.9
XS Rating Curve= 0 ,0
Exp/Cntr=0.3,0.1

Type RM Length L Ch R = 1 ,6697.2  ,326,335.2,344.2
XS GIS Cut Line= 2
     1550112.586      364091.528     1550268.025      364431.038
#Sta/Elev= 24
    10.1  711.67    70.6  678.42   100.9  662.07     111  656.41   121.1   650.1
   131.2  642.97   141.3   634.8   151.4  625.65   161.5  618.72   164.1  618.17
   171.6   616.6   179.1  617.01   181.7  617.15   242.2  623.26   252.3  624.19
   262.4  624.91   272.5   625.5   302.8  626.84   322.9  627.96     333  628.26
   343.1  628.42   353.2  628.82   363.3  629.86   373.4  631.42
#Mann= 3 , 0 , 0
       0      .1       0   164.1    .045       0   179.1      .1       0
Bank Sta=164.1,179.1
XS Rating Curve= 0 ,0
Exp/Cntr=0.3,0.1

Type RM Length L Ch R = 1 ,6362    ,373.8,375.4,376.9
XS GIS Cut Line= 2
     1549944.877      364128.342     1549998.053      364647.834
#Sta/Elev= 30
      10  728.81    30.1  720.72    50.2  712.07    60.3  707.41    90.4  692.63
   100.4  687.38   110.5   681.7   120.5  675.44   130.6  668.59   150.6  654.05
   160.7  647.25   170.7  641.54   180.8  637.05   210.9   625.6   220.9  622.78
     231  621.24   311.3  616.35   333.9  614.13   341.4  613.55   348.9  613.91
   351.5  614.04   361.5  617.54   371.6  623.96   381.6  629.29   401.7  634.09
   421.8  641.28   441.9  648.96     462  656.97   512.2  678.05   522.2  682.45
#Mann= 3 , 0 , 0
       0      .1       0   333.9    .045       0   348.9     .08       0
Bank Sta=333.9,348.9
XS Rating Curve= 0 ,0
Exp/Cntr=0.3,0.1

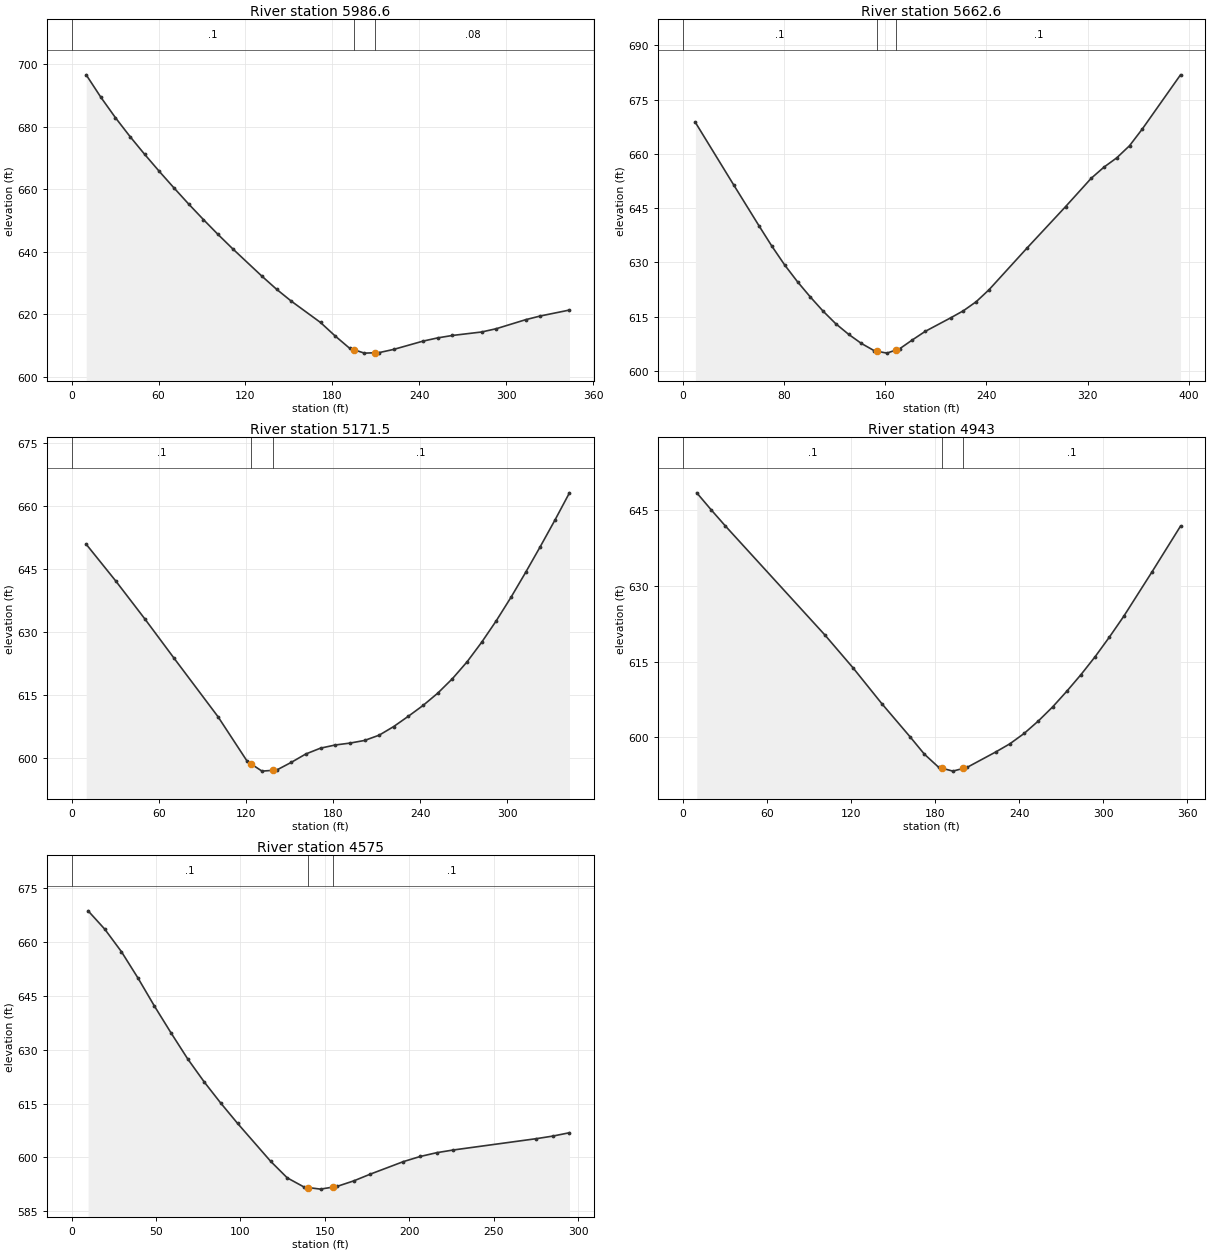
Type RM Length L Ch R = 1 ,5986.6  ,319.7,324,328.4
XS GIS Cut Line= 2
     1549600.384      364290.973     1549612.127      364634.383
#Sta/Elev= 30
    10.1  696.53    20.2  689.38    30.3  682.83    40.4  676.79    50.5  671.11
    60.6  665.67    70.7  660.41    80.8  655.28      91  650.31   101.1  645.55
   111.2  640.98   131.4  632.22   141.5  628.05   151.6  624.27   171.8  617.45
   181.9  613.14     192  609.17   194.6  608.78   202.1  607.66   209.6  607.78
   212.2  607.82   222.3  608.85   242.5  611.49   252.7  612.53   262.8   613.3
     283  614.41   293.1  615.46   313.3  618.33   323.4  619.51   343.6  621.42
#Mann= 3 , 0 , 0
       0      .1       0   194.6    .045       0   209.6     .08       0
Bank Sta=194.6,209.6
XS Rating Curve= 0 ,0
Exp/Cntr=0.3,0.1

Type RM Length L Ch R = 1 ,5662.6  ,422.7,491.2,494.5
XS GIS Cut Line= 2
     1549310.851      364341.048     1549249.494      364729.644
#Sta/Elev= 30
    10.1  668.68    40.3  651.44    60.5  640.02    70.6  634.43    80.7  629.24
    90.8  624.62   100.9  620.42     111   616.5     121  613.02   131.1  610.11
   141.2  607.58   151.3  605.58   153.9   605.4   161.4  604.89   168.9  605.79
   171.5   606.1   181.6  608.56   191.7  610.91   211.8  614.65   221.9  616.62
     232  619.12   242.1  622.42   272.4  634.06   302.6  645.41   322.8  653.23
   332.9  656.32     343  658.89   353.1  662.24   363.1  666.82   393.4  681.85
#Mann= 3 , 0 , 0
       0      .1       0   153.9    .045       0   168.9      .1       0
Bank Sta=153.9,168.9
XS Rating Curve= 0 ,0
Exp/Cntr=0.3,0.1

Type RM Length L Ch R = 1 ,5171.5  ,224.7,228.4,232.1
XS GIS Cut Line= 2
     1549036.788      364271.509     1548922.255      364594.658
#Sta/Elev= 30
    10.1  650.87    30.3   642.2    50.4  633.15    70.6  623.77   100.8  609.89
     121  599.24   123.6  598.65   131.1  596.94   138.6  597.13   141.2  597.19
   151.3  599.03   161.3  601.02   171.4   602.4   181.5  603.15   191.6   603.6
   201.7  604.23   211.8  605.49   221.8  607.54   231.9  609.99     242  612.55
   252.1  615.47   262.2  618.91   272.3  622.92   282.3  627.55   292.4  632.68
   302.5  638.24   312.6  644.17   322.7  650.31   332.8  656.62   342.8   663.1
#Mann= 3 , 0 , 0
       0      .1       0   123.6    .045       0   138.6      .1       0
Bank Sta=123.6,138.6
XS Rating Curve= 0 ,0
Exp/Cntr=0.3,0.1

Type RM Length L Ch R = 1 ,4943    ,367.5,368.1,368.9
XS GIS Cut Line= 2
     1548864.988      364169.247     1548693.187      364480.124
#Sta/Elev= 25
    10.1  648.39    20.3  645.05    30.4  641.86   101.5  620.25   121.8  613.67
   142.1  606.66   162.4  600.05   172.5  596.65   182.7  594.05   185.3  593.86
   192.8   593.3   200.3  593.85     203  594.05   223.3  597.08   233.4   598.7
   243.6  600.75   253.7  603.21   263.9  605.99     274  609.09   284.2  612.41
   294.3  615.96   304.4  619.81   314.6  623.91   334.9  632.76   355.2   641.8
#Mann= 3 , 0 , 0
       0      .1       0   185.3    .045       0   200.3      .1       0
Bank Sta=185.3,200.3
XS Rating Curve= 0 ,0
Exp/Cntr=0.3,0.1

Type RM Length L Ch R = 1 ,4575    ,4589.2,4575,4557.5
XS GIS Cut Line= 2
     1548615.468      364030.171     1548472.301      364287.871
#Sta/Elev= 26
     9.8  668.71    19.7  663.58    29.5  657.35    39.3  650.01    49.1  642.15
      59  634.63    68.8  627.44    78.6  621.01    88.4  615.12    98.3   609.5
   117.9  598.93   127.7  594.33   137.6  591.79   139.9  591.64   147.4  591.19
   154.9  591.77   157.2  591.95   167.1  593.49   176.9  595.37   196.5  598.86
   206.4  600.28   216.2  601.34     226  602.09   275.1  605.24     285  605.97
   294.8   606.9
#Mann= 3 , 0 , 0
       0      .1       0   139.9    .045       0   154.9      .1       0
Bank Sta=139.9,154.9
XS Rating Curve= 0 ,0
Exp/Cntr=0.3,0.1

Chan Stop Cuts=-1
Use User Specified Reach Order=0